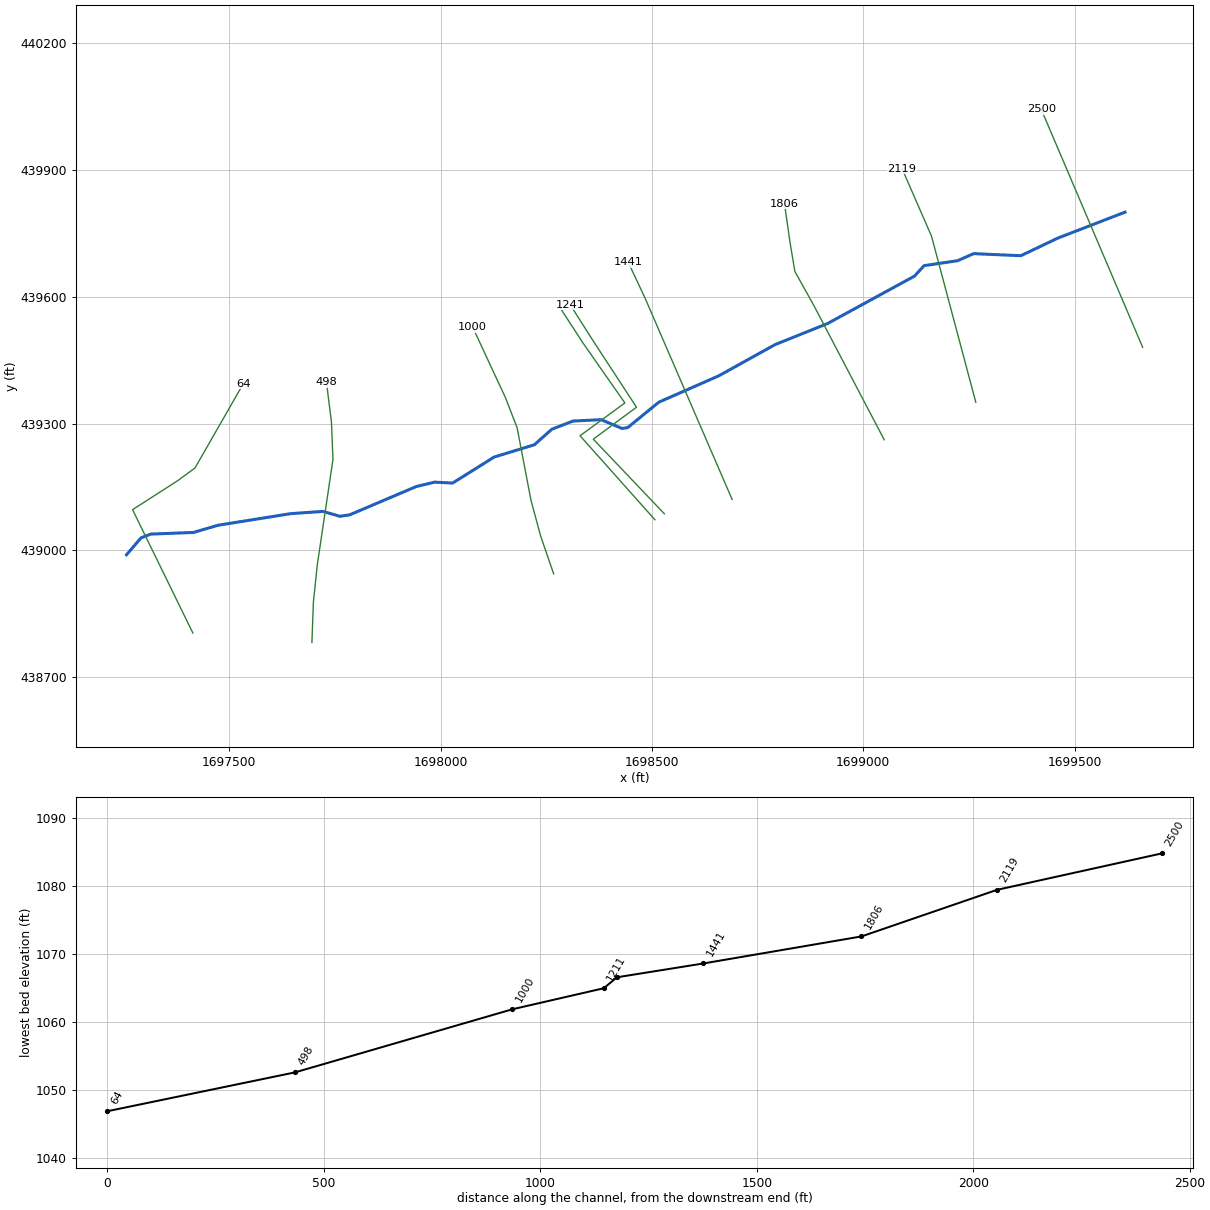
--- RCKCMPRNT1.prj (project) ---

Proj Title=RCKCMPRNT1
Current Plan=p01
Default Exp/Contr=0,0
English Units
Geom File=g01
Flow File=f01
Plan File=p01
BEGIN DESCRIPTION:
---------- MODELED AS PART OF WVEMD CTP PROGRAM, 2023----------
Stream Name: Rockcamp Run Tributary 1
Flood Zone:  AFH
Wetzel County, WV
HEC-RAS Version: RAS 6.3
Vertical Datum: NAVD88
Projection: NAD 1983 StatePlane West Virginia S FIPS 4702 (US Feet)
Terrain: 1-meter West Virginia FEMA R3 South Central (collected 2018-2020)
Land Use: 2019 NLCD
Hydrologic Method:
WV SIR2010-5033 regression equations
Additional Model Notes:
None
END DESCRIPTION:
DSS Export Rating Curves= 0
DSS Export Rating Curve Sorted= 0
DSS Export Volume Flow Curves= 0
DXF OffsetX= 0
DXF OffsetY= 0
DXF ScaleX= 0
DXF ScaleY= 0

--- RCKCMPRNT1.p01 (plan) ---

Plan Title=Floodplain
Program Version=6.30
Short Identifier=Floodplain
Geom File=g01
Flow File=f01
Subcritical Flow
K Sum by GR= 0
Std Step Tol= 0.01
Critical Tol= 0.01
Num of Std Step Trials= 20
Max Error Tol= 0.3
Flow Tol Ratio= 0.001
Split Flow NTrial= 30
Split Flow Tol= 0.02
Split Flow Ratio= 0.02
Log Output Level= 0
Friction Slope Method= 1
Unsteady Friction Slope Method= 2
Unsteady Bridges Friction Slope Method= 1
Parabolic Critical Depth
Global Vel Dist= 0 , 0 , 0
Global Log Level= 0
CheckData=True
Encroach Param=-1 ,0,0, 0
Mapping Interval=1HOUR
Computation Time Step Use Courant=        0
Computation Time Step Use Time Series=    0
Computation Time Step Count To Double=0
Computation Time Step Max Doubling=0
Computation Time Step Max Halving=0
Computation Time Step Residence Courant=0
Run HTab= 0
Run UNet= 0
Run Sediment= 0
Run PostProcess= 0
Run WQNet= 0
Run RASMapper= 0
UNET Theta= 0
UNET Theta Warmup= 0
UNET ZTol= 0
UNET ZSATol= 0
UNET MxIter= 0
UNET Max Iter WO Improvement= 0
UNET MaxInSteps= 0
UNET DtIC= 0
UNET DtMin= 0
UNET MaxCRTS= 0
UNET WFStab= 0
UNET SFStab= 0
UNET WFX= 1
UNET SFX= 1
UNET Gravity=32.17405
UNET 1D Methodology=Finite Difference
UNET DSS MLevel= 1
UNET Pardiso=0
UNET DZMax Abort= 0
UNET Use Existing IB Tables= 0
UNET Froude Reduction=False
UNET Froude Limit= 0
UNET Froude Power= 0
UNET D1 Cores= 0
UNET WindReference=Eulerian
UNET WindDragFormulation=Hsu (1988)
UNET D2 Coriolis=0
UNET D2 Cores= 0
UNET D2 Theta= 1
UNET D2 Theta Warmup= 1
UNET D2 Z Tol= 0.01
UNET D2 Volume Tol= 0.01
UNET D2 Max Iterations= 20
UNET D2 Equation= 0
UNET D2 RampUpFraction=0.1
UNET D2 TimeSlices= 1
UNET D2 Turbulence Formulation=Non-Conservative (original)
UNET D2 Eddy Viscosity=0.3
UNET D2 Transverse Eddy Viscosity=0.1
UNET D2 Smagorinsky Mixing=0
UNET D2 BCVolumeCheck=0
UNET D2 Cores=0
UNET D2 SolverType=PARDISO (Direct)
UNET D2 Minimum Iterations= 3
UNET D2 Maximum Iterations= 30
UNET D2 Restart Number= 10
UNET D2 Relaxation Coeff=1.3
UNET D2 SOR Precondition Iterations= 10
UNET D2 ILUT Maximum Fill= 8
UNET D2 ILUT Tolerance=1E-08
UNET D2 Convergence Tolerance=0.00001
UNET D1D2 MaxIter= 0
UNET D1D2 ZTol=0.01
UNET D1D2 QTol=0.1
UNET D1D2 MinQTol=1
Write IC File= 0
Write IC File at Fixed DateTime=0
Write IC File at Sim End=0
Echo Input=False
Echo Parameters=False
Echo Output=False
Write Detailed= 0
HDF Write Warmup=0
HDF Write Time Slices=0
HDF Flush=0
HDF Compression= 1
HDF Chunk Size= 1
HDF Spatial Parts= 1
HDF Use Max Rows=0
HDF Fixed Rows= 1
Calibration Method= 0
Calibration Iterations= 20
Calibration Max Change=0.05
Calibration Tolerance=0.2
Calibration Maximum=1.5
Calibration Minimum=0.5
Calibration Optimization Method= 1
WQ AD Non Conservative
WQ ULTIMATE=-1
WQ Max Comp Step=1HOUR
WQ Output Interval=15MIN
WQ Output Selected Increments= 0
WQ Output face flow=0
WQ Output face velocity=0
WQ Output face area=0
WQ Output face dispersion=0
WQ Output cell volume=0
WQ Output cell surface area=0
WQ Output cell continuity=0
WQ Output cumulative cell continuity=0
WQ Output face conc=0
WQ Output face dconc_dx=0
WQ Output face courant=0
WQ Output face peclet=0
WQ Output face adv mass=0
WQ Output face disp mass=0
WQ Output cell mass=0
WQ Output cell source sink temp=0
WQ Output nsm pathways=0
WQ Output nsm derived pathways=0
WQ Create Restart=0
WQ Fixed Restart=0
WQ System Summary=0
WQ Write To DSS=0
Sorting and Armoring Iterations= 10
XS Update Threshold= 0.02
Bed Roughness Predictor= 0
Hydraulics Update Threshold= 0.02
Energy Slope Method= 1
Volume Change Method= 1
Sediment Retention Method= 0
Sediment TS Multiplier= 1
Warm Up Method= 0
XS Weighting Method= 0
Number of US Weighted Cross Sections= 1
Number of DS Weighted Cross Sections= 1
Upstream XS Weight=0
Main XS Weight=1
Downstream XS Weight=0
Number of DS XS's Weighted with US Boundary= 1
Upstream Boundary Weight= 1
Weight of XSs Associated with US Boundary= 0
Number of US XS's Weighted with DS Boundary= 1
Downstream Boundary Weight= 0.5
Weight of XSs Associated with DS Boundary= 0.5
Percentile Method= 0
Sediment Output Level= 3
Mass or Volume Output= 0
Output Increment Type= 1
Profile and TS Output Increment= 1
Transport Output Increment 1
XS Output Flag= 0
XS Output Increment= 10
Read HDF5 Sediment Hotstart= 0
Sediment Hotstart Type= 0
Write Gradation File= 0
Read Gradation Hotstart= 0
Write HDF5 File= 1
Write Binary Output= 1
Write DSS Sediment File= 0
DSS Sediment Output Type= 1
SV Curve= 0
Specific Gage Flag= 0
Subcell Erosion Methods= 0
Subcell Deposition Methods= 0
Advection Scheme= 1
Matrix Solver= 0
Implicit Weighting Factor= 1
Maximum Outer Loop Convergence Iterations= 5
Convergence Maximum Absolute= 0.001
Convergence RMSE= 0.0001
Grain Fractions Max Abs Error= 0.001
Max Subgrid Regions= 1
Max Subgrid Length Scale= 3.402823E+38
Initial Layer Thickness= 3.402823E+38
Min Layer Thickness= 3.402823E+38
Max Layer Thickness= 3.402823E+38
Number of Layers= 5

--- RCKCMPRNT1.f01 (steady flow) ---

Flow Title=Flow
Program Version=4.00
Number of Profiles=1
Profile Names=F01pct
River Rch & RM=RCKCMPRNT1,Main,2500
     622
Boundary for River Rch & Prof#=RCKCMPRNT1,Main      ,1
Up Type=0
Dn Type=3
Dn Slope=0.01696

--- RCKCMPRNT1.g01 (geometry) ---

Geom Title=Geometry
Program Version=6.30

River Reach=RCKCMPRNT1      ,Main
Reach XY= 30
1699619.40638015439800.5093695211699460.65270813439739.163174856
     1699372.939      439697.394     1699261.461      439702.324
     1699223.388      439685.616     1699143.957      439673.838
     1699121.497      439649.187     1698915.796      439536.887
     1698791.718      439487.037     1698658.327      439413.083
     1698516.446      439350.633     1698442.766      439290.375
     1698429.345      439288.457     1698380.042      439309.274
     1698313.484      439305.987     1698263.634      439286.814
     1698222.001      439249.837     1698126.957      439220.804
     1698028.625      439159.175      1697986.17      439161.367
      1697942.62      439150.958     1697784.852      439083.852
     1697761.845      439080.565     1697722.129      439092.069
     1697645.333      439086.745     1697473.716      439059.355
     1697415.512      439042.236      1697314.51      439038.384
       1697291.4      439029.397     1697257.038      438989.414

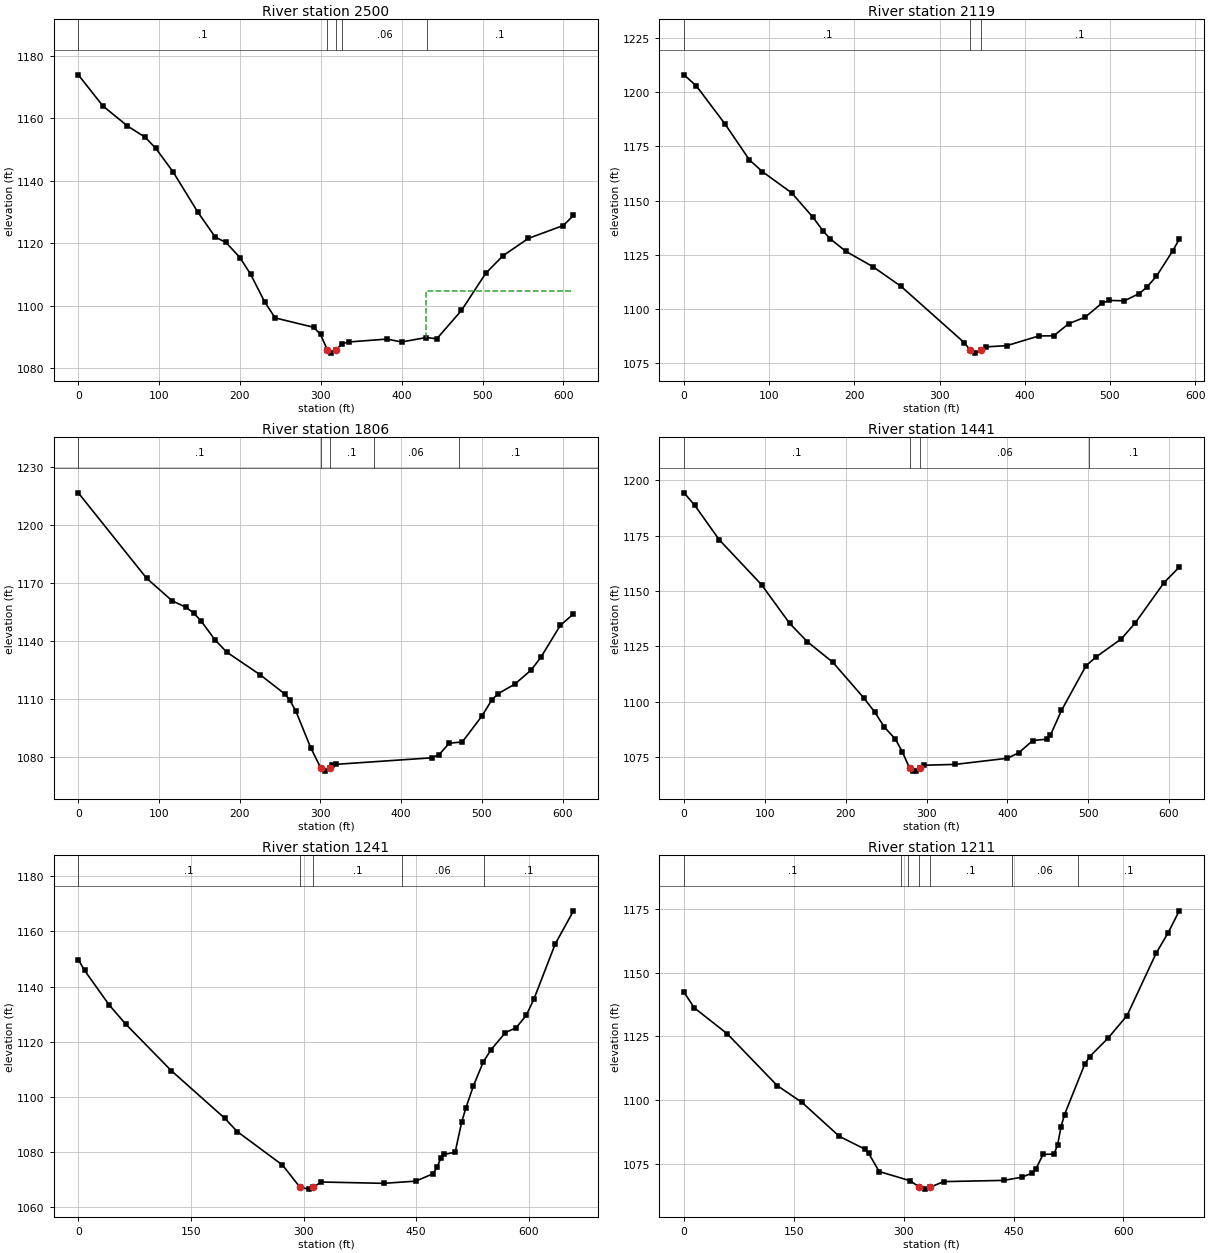
Type RM Length L Ch R = 1 ,2500    ,380.8,380.7,379
XS GIS Cut Line= 6
1699661.20389175439480.5806543381699624.46741667439566.833434582
1699590.17975558439647.3355701711699521.60410534439808.339841336
1699457.92641117439957.8434793351699421.19026418440044.096259594
#Sta/Elev= 30
       0 1173.98    30.4 1164.01    60.8 1157.59    82.6    1154    95.6 1150.51
   117.3 1142.86   147.8    1130   169.5 1121.95   182.6 1120.29   199.9 1115.44
     213 1110.15   230.4 1101.29   243.4  1096.1   291.2 1093.08   299.6  1090.8
  307.921085.923     313 1084.81   319.2 1085.94     326 1087.81   334.7 1088.39
   381.9 1089.31   399.9 1088.38   430.4 1089.81   443.4  1089.4   473.9 1098.47
   503.9 1110.37   525.2 1115.99   556.5 1121.55   599.9  1125.7   612.5 1128.93
#Mann= 5 ,-1,0
       0      .1       0  307.92    .045       0   319.2      .1       0
  326.25     .06       0  431.25      .1       0
#XS Ineff= 2 , 0
                          429.76         1104.83
Permanent Ineff=
       F       F
Bank Sta=307.92,319.2
XS Rating Curve= 0 ,0
Exp/Cntr(USF)=0,0
Exp/Cntr=0.3,0.1

Type RM Length L Ch R = 1 ,2119    ,311.4,312.9,314
XS GIS Cut Line= 3
1699266.41162692 439350.446359331699161.73478575439743.497635466
1699091.95022498439903.591627835
#Sta/Elev= 30
       0  1208.1    14.6 1202.89    47.7 1185.58    76.7 1168.81    91.8 1163.39
   126.3 1153.55   151.2 1142.33   163.6 1135.73   171.9 1132.17   189.9 1126.53
   221.6 1119.44   254.7 1110.34   329.2 1084.21  336.26 1080.68   341.6 1079.45
  348.67 1080.68     354 1082.32   378.9 1082.91   416.6 1087.39   434.1 1087.47
   451.5 1093.04   470.9 1096.07   490.8 1102.61   499.5  1103.8     517 1103.64
   534.4 1106.97   543.2 1109.89   554.6 1114.98   573.7  1126.7   581.4  1132.1
#Mann= 3 ,-1,0
       0      .1       0  336.26    .045       0  348.67      .1       0
Bank Sta=336.26,348.67
XS Rating Curve= 0 ,0
Exp/Cntr(USF)=0,0
Exp/Cntr=0.3,0.1

Type RM Length L Ch R = 1 ,1806    ,365.6,365.5,364.6
XS GIS Cut Line= 6
1699049.74860751439261.7419567481699006.18045318439344.730963997
1698884.46022418439577.304645829 1698838.3947119439660.174212737
1698826.58958475439731.0218468251698813.81463652439820.600069605
#Sta/Elev= 30
       0 1216.66    84.5  1172.5   116.1 1160.81   133.6 1157.37   143.2 1154.31
   152.2 1150.27   169.2  1140.6   183.8 1134.23   225.5 1122.41     256 1112.47
   262.1 1109.26   269.6 1103.54   287.8 1084.82  300.39 1074.18   305.7  1072.6
   311.5  1074.2   314.7 1075.75   319.2 1076.12   437.7 1079.49   446.9 1081.12
   459.5 1087.06   475.7  1087.7   500.1 1101.18   512.2 1109.44   520.3 1112.76
   540.6 1117.59   560.8 1124.86   572.9 1131.44   597.1 1148.07   613.4 1153.94
#Mann= 5 ,-1,0
       0      .1       0  300.39    .045       0   311.5      .1       0
  366.23     .06       0  471.04      .1       0
Bank Sta=300.39,311.5
XS Rating Curve= 0 ,0
Exp/Cntr(USF)=0,0
Exp/Cntr=0.3,0.1

Type RM Length L Ch R = 1 ,1441    ,210.2,199.3,188.4
BEGIN DESCRIPTION:
Structure XS 4
END DESCRIPTION:
XS GIS Cut Line= 6
1698689.88893878439120.5157576651698588.24609744439355.744617924
1698548.58082244439447.5413503351698518.83088194439516.388653591
1698484.12524269439596.7116556761698444.18404961439681.623231262
#Sta/Elev= 30
       0 1194.31    13.1 1188.72    43.6 1173.07    95.9 1152.79   130.7 1135.32
   152.5 1127.07   183.9 1117.83   222.3  1101.7   235.7 1095.38   247.8 1088.49
   261.5 1083.05   270.2 1077.19   278.9 1070.06   283.3 1068.69   286.8 1068.62
     292 1070.01   296.3 1071.27   335.5 1071.66     400 1074.43     414 1076.88
   431.4 1082.44   448.8 1083.06   453.2 1084.82   466.9 1096.03   497.3 1116.21
   509.8 1120.23   540.7 1128.27   557.7 1135.32   593.7  1153.7   612.6 1160.77
#Mann= 4 ,-1,0
       0      .1       0   278.9    .045       0     292     .06       0
  501.25      .1       0
Bank Sta=278.9,292
XS Rating Curve= 0 ,0
Exp/Cntr(USF)=0,0
Exp/Cntr=0.3,0.1

Type RM Length L Ch R = 1 ,1241    ,30.3,30.3,31.5
BEGIN DESCRIPTION:
Structure XS 3
END DESCRIPTION:
XS GIS Cut Line= 5
1698529.47295248439086.5585849881698361.48343565439263.110658703
1698463.72442843439338.7598072111698363.21980465439492.569478172
1698306.99288287439581.028112466
#Sta/Elev= 30
       0 1149.77     8.3 1145.84    41.4 1133.21    63.5 1126.28   123.8 1109.52
   194.8 1092.32   211.7 1087.44   271.9 1075.31   295.2 1067.28   306.6 1066.59
  312.581067.271   323.8 1069.17   406.7 1068.69   449.5 1069.49   472.6 1072.19
   478.1 1074.73   482.9 1077.95   487.2 1079.17   501.8 1079.96   510.6 1090.97
   516.2 1096.06   525.9 1103.83   539.5 1112.79   549.8 1117.15   568.8 1123.33
     583 1125.05   596.5 1129.56   606.7 1135.44   635.1 1155.42   659.4 1167.42
#Mann= 5 ,-1,0
       0      .1       0   295.2    .045       0  312.58      .1       0
  430.89     .06       0  540.89      .1       0
Bank Sta=295.2,312.58
XS Rating Curve= 0 ,0
Exp/Cntr(USF)=0,0
Exp/Cntr=0.3,0.1

Type RM Length L Ch R = 1 ,1211    ,202.3,210.9,215.6
BEGIN DESCRIPTION:
Structure XS 2
END DESCRIPTION:
XS GIS Cut Line= 5
1698507.30334436439072.3041918931698330.08228867439271.237630272
1698436.27438277439348.811489441 1698336.6731176439491.358614568
 1698279.8779129439578.935760099
#Sta/Elev= 30
       0 1142.26    13.8 1136.17    59.1 1125.91   127.1 1105.64     161 1099.02
   212.1 1085.69   246.7 1080.71   252.1 1079.02   266.4 1071.89   308.6 1068.28
  321.131065.803   328.4 1064.98   336.4  1065.8   354.7 1067.93   436.6 1068.41
     461 1069.65   475.7 1071.29   480.6 1073.02   490.3 1078.63     505 1078.71
     510 1082.17   514.7 1089.42   519.6 1094.26   547.2 1114.06   553.7 1116.95
   578.9 1124.21   604.9 1133.09   644.7  1157.6   661.1 1165.64   676.2 1174.21
#Mann= 7 ,-1,0
       0      .1       0  296.42     .06       0  306.42      .1       0
  321.13    .045       0   336.4      .1       0  447.93     .06       0
  537.93      .1       0
Bank Sta=321.13,336.4
XS Rating Curve= 0 ,0
Exp/Cntr(USF)=0,0
Exp/Cntr=0.3,0.1

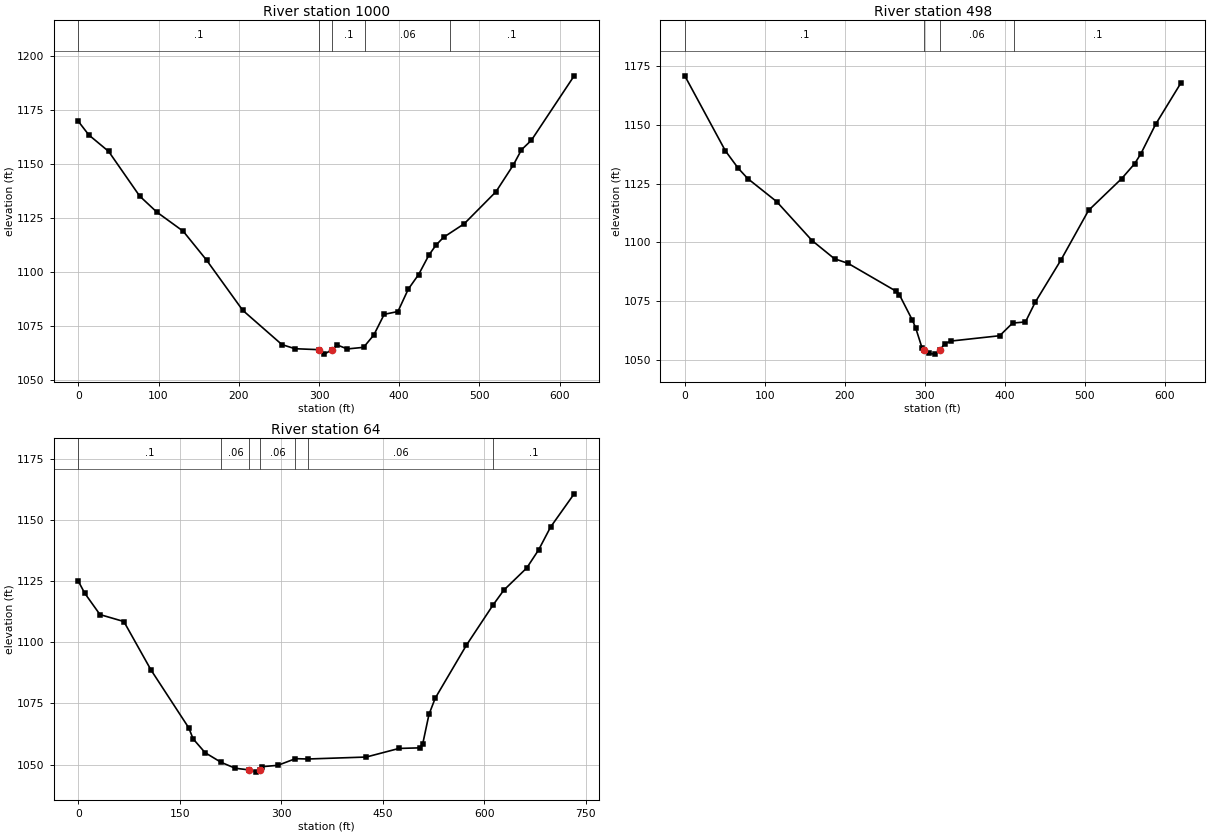
Type RM Length L Ch R = 1 ,1000    ,505.8,501.9,498.3
BEGIN DESCRIPTION:
Structure XS 1
END DESCRIPTION:
XS GIS Cut Line= 6
1698267.72013018438944.1670290081698236.99873492439033.525774166
1698214.09228468439118.2322976741698181.25803275439290.124670416
1698153.76957068439361.085158423  1698075.924582439528.660610676
#Sta/Elev= 30
       0 1169.78    13.1 1163.47    37.8 1155.84    76.5 1135.13    97.9 1127.71
   130.8 1118.83   159.8 1105.49   204.9 1082.22   253.8 1066.31   270.1  1064.4
   299.4 1063.96   306.8 1061.89  315.971063.904     323 1066.09   335.3 1064.29
   355.6 1065.04   368.4 1070.79   381.3 1080.34   398.4 1081.63   411.3 1092.01
   424.2 1098.77   437.1 1107.84   445.9 1112.43   455.3 1116.04   481.1 1122.33
   520.6 1137.15   542.4 1149.64   552.4  1156.6   564.8 1161.02   618.1 1190.88
#Mann= 5 ,-1,0
       0      .1       0   299.4    .045       0  315.97      .1       0
  357.24     .06       0  463.34      .1       0
Bank Sta=299.4,315.97
XS Rating Curve= 0 ,0
Exp/Cntr(USF)=0,0
Exp/Cntr=0.3,0.1

Type RM Length L Ch R = 1 ,498     ,428.1,433.8,439
XS GIS Cut Line= 6
 1697695.7366941438781.8871698381697699.26457417438877.108107999
1697708.48076309 438965.524269761697745.53449476439215.067077756
1697742.02269076439303.2998409271697730.18445984439397.622815013
#Sta/Elev= 30
       0 1170.69    50.7 1138.89    66.7 1131.51    78.7 1127.09   114.8 1117.34
   159.1  1100.8   187.2 1093.05     204 1091.15   264.2  1079.3   268.2 1077.86
   284.4 1067.11   288.5  1063.9   296.6 1055.25  298.771054.353   304.7  1052.9
   312.9 1052.61     319 1054.38     325 1057.04   333.1 1058.17   393.7 1060.42
   409.8 1065.78   425.9 1066.27     438 1074.56   470.1 1092.44   504.8 1113.61
   546.2 1127.09   562.4  1133.4   570.2 1137.62   588.5 1150.04   619.9 1167.47
#Mann= 4 ,-1,0
       0      .1       0  298.77    .045       0     319     .06       0
  411.52      .1       0
Bank Sta=298.77,319
XS Rating Curve= 0 ,0
Exp/Cntr(USF)=0,0
Exp/Cntr=0.3,0.1

Type RM Length L Ch R = 1 ,64      ,,,
XS GIS Cut Line= 5
1697414.17537579438804.078563997 1697271.4606676439096.145873776
1697378.49669874439165.0140178431697419.15379584439194.884538161
1697533.65745706439394.851076959
#Sta/Elev= 30
       0 1124.98     9.4  1120.1      32 1111.33    67.3 1108.49   107.4  1088.7
   163.4 1064.95   169.7 1060.51   187.5 1054.84   211.2 1050.89     232 1048.48
   253.1 1047.78   263.2 1046.89   268.1 1047.79   272.1 1049.13     295 1049.67
   321.1  1052.4   339.3 1052.26   425.7 1053.06   474.2 1056.58   504.7 1056.82
   509.3 1058.48   518.5 1070.48   527.7 1077.11   573.8 1098.78   613.2 1115.23
   629.2 1121.33     663 1130.37   680.6 1137.77   698.3 1147.12   733.2 1160.72
#Mann= 7 ,-1,0
       0      .1       0   211.2     .06       0   253.1    .045       0
   268.1     .06       0   321.1      .1       0   339.3     .06       0
   613.2      .1       0
Bank Sta=253.1,268.1
XS Rating Curve= 0 ,0
Exp/Cntr(USF)=0,0
Exp/Cntr=0.3,0.1
LCMann Table=0

Chan Stop Cuts=-1
Use User Specified Reach Order=0
Composite Channel Slope=5